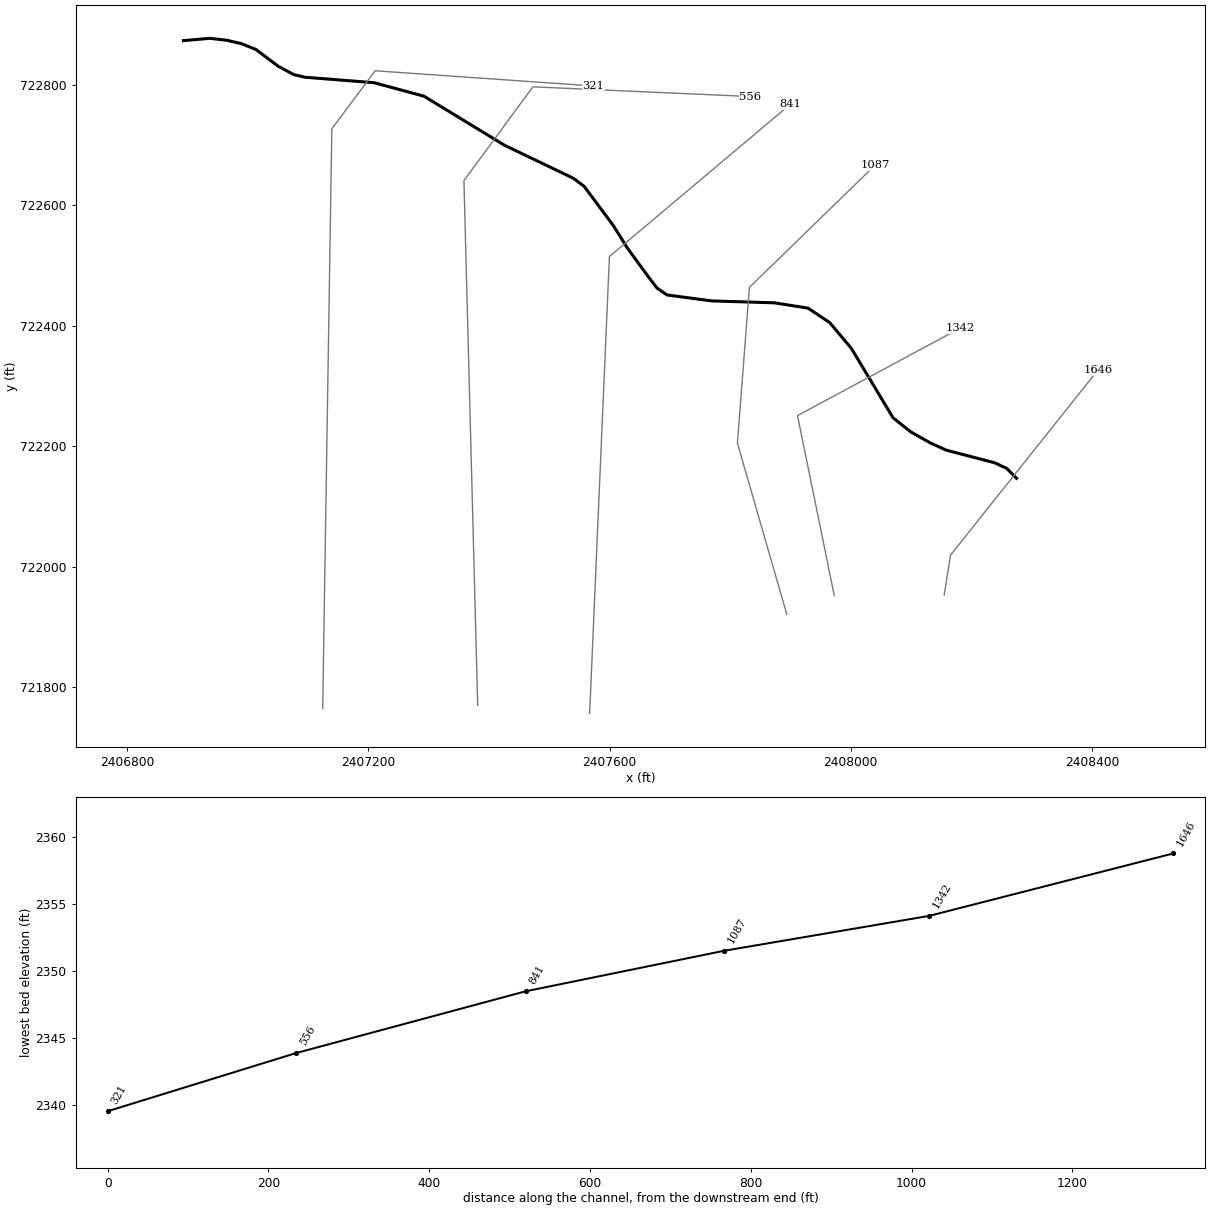
--- COLLINSRN.prj (project) ---

Proj Title=COLLINSRN
Current Plan=p01
Default Exp/Contr=0,0
English Units
Geom File=g01
Flow File=f01
Plan File=p01
BEGIN DESCRIPTION:
----------MODEL BY WOOD PLC 2022----------
AFH study
Randolph County, WV
HEC-RAS Version: RAS 6.2
Vertical Datum: NAVD88
Projection: NAD 1983 StatePlane West Virginia S FIPS 4702 (US Feet)
Terrain: 1-meter LIDAR (FEMA Region III 3DEP collected 2016-2018)
Land Use: 2019 NLCD
Hydrologic Method:
WV SIR2010-5033 regression equations
Additional Model Notes:
Mapping to trim floodplain because the backwater from REDCK dominates
END DESCRIPTION:
DSS Export Rating Curves= 0
DSS Export Rating Curve Sorted= 0
DSS Export Volume Flow Curves= 0
DXF OffsetX= 0
DXF OffsetY= 0
DXF ScaleX= 0
DXF ScaleY= 0

--- COLLINSRN.p01 (plan) ---

Plan Title=Floodplain
Program Version=6.20
Short Identifier=Floodplain
Geom File=g01
Flow File=f01
Subcritical Flow
K Sum by GR= 0
Std Step Tol= 0.01
Critical Tol= 0.01
Num of Std Step Trials= 20
Max Error Tol= 0.3
Flow Tol Ratio= 0.001
Split Flow NTrial= 30
Split Flow Tol= 0.02
Split Flow Ratio= 0.02
Log Output Level= 0
Friction Slope Method= 1
Unsteady Friction Slope Method= 2
Unsteady Bridges Friction Slope Method= 1
Parabolic Critical Depth
Global Vel Dist= 0 , 0 , 0
Global Log Level= 0
CheckData=True
Encroach Param=-1 ,0,0, 0
Mapping Interval=1HOUR
Computation Time Step Use Courant=        0
Computation Time Step Use Time Series=    0
Computation Time Step Count To Double=0
Computation Time Step Max Doubling=0
Computation Time Step Max Halving=0
Computation Time Step Residence Courant=0
Run HTab= 0
Run UNet= 0
Run Sediment= 0
Run PostProcess= 0
Run WQNet= 0
Run RASMapper= 0
UNET Theta= 0
UNET Theta Warmup= 0
UNET ZTol= 0
UNET ZSATol= 0
UNET MxIter= 0
UNET Max Iter WO Improvement= 0
UNET MaxInSteps= 0
UNET DtIC= 0
UNET DtMin= 0
UNET MaxCRTS= 0
UNET WFStab= 0
UNET SFStab= 0
UNET WFX= 1
UNET SFX= 1
UNET Gravity=32.174
UNET 1D Methodology=Finite Difference
UNET DSS MLevel= 1
UNET Pardiso=0
UNET DZMax Abort= 0
UNET Use Existing IB Tables= 0
UNET Froude Reduction=False
UNET Froude Limit= 0
UNET Froude Power= 0
UNET D1 Cores= 0
UNET WindReference=Eulerian
UNET WindDragFormulation=Hsu (1988)
UNET D2 Coriolis=0
UNET D2 Cores= 0
UNET D2 Theta= 1
UNET D2 Theta Warmup= 1
UNET D2 Z Tol= 0.01
UNET D2 Volume Tol= 0.01
UNET D2 Max Iterations= 20
UNET D2 Equation= 0
UNET D2 RampUpFraction=0.1
UNET D2 TimeSlices= 1
UNET D2 Turbulence Formulation=Non-Conservative (original)
UNET D2 Eddy Viscosity=0.3
UNET D2 Transverse Eddy Viscosity=0.1
UNET D2 Smagorinsky Mixing=0
UNET D2 BCVolumeCheck=0
UNET D2 Cores=0
UNET D2 SolverType=PARDISO (Direct)
UNET D2 Minimum Iterations= 2147483647
UNET D2 Maximum Iterations= 2147483647
UNET D2 Restart Number= 10
UNET D2 Relaxation Coeff=1.3
UNET D2 SOR Precondition Iterations= 10
UNET D2 ILUT Maximum Fill= 8
UNET D2 ILUT Tolerance=1E-08
UNET D1D2 MaxIter= 0
UNET D1D2 ZTol=0.01
UNET D1D2 QTol=0.1
UNET D1D2 MinQTol=1
Write IC File= 0
Write IC File at Fixed DateTime=0
Write IC File at Sim End=0
Echo Input=False
Echo Parameters=False
Echo Output=False
Write Detailed= 0
HDF Write Warmup=0
HDF Write Time Slices=0
HDF Flush=0
HDF Compression= 1
HDF Chunk Size= 1
HDF Spatial Parts= 1
HDF Use Max Rows=0
HDF Fixed Rows= 1
Calibration Method= 0
Calibration Iterations= 20
Calibration Max Change=0.05
Calibration Tolerance=0.2
Calibration Maximum=1.5
Calibration Minimum=0.5
Calibration Optimization Method= 1
WQ AD Non Conservative
WQ ULTIMATE=-1
WQ Max Comp Step=1HOUR
WQ Output Interval=15MIN
WQ Output Selected Increments= 0
WQ Output face flow=0
WQ Output face velocity=0
WQ Output face area=0
WQ Output face dispersion=0
WQ Output cell volume=0
WQ Output cell surface area=0
WQ Output cell continuity=0
WQ Output cumulative cell continuity=0
WQ Output face conc=0
WQ Output face dconc_dx=0
WQ Output face courant=0
WQ Output face peclet=0
WQ Output face adv mass=0
WQ Output face disp mass=0
WQ Output cell mass=0
WQ Output cell source sink temp=0
WQ Output nsm pathways=0
WQ Output nsm derived pathways=0
WQ Create Restart=0
WQ Fixed Restart=0
WQ System Summary=0
WQ Write To DSS=0
Sorting and Armoring Iterations= 10
XS Update Threshold= 0.02
Bed Roughness Predictor= 0
Hydraulics Update Threshold= 0.02
Energy Slope Method= 1
Volume Change Method= 1
Sediment Retention Method= 0
Sediment TS Multiplier= 1
Warm Up Method= 0
XS Weighting Method= 0
Number of US Weighted Cross Sections= 1
Number of DS Weighted Cross Sections= 1
Upstream XS Weight=0
Main XS Weight=1
Downstream XS Weight=0
Number of DS XS's Weighted with US Boundary= 1
Upstream Boundary Weight= 1
Weight of XSs Associated with US Boundary= 0
Number of US XS's Weighted with DS Boundary= 1
Downstream Boundary Weight= 0.5
Weight of XSs Associated with DS Boundary= 0.5
Percentile Method= 0
Sediment Output Level= 3
Mass or Volume Output= 0
Output Increment Type= 1
Profile and TS Output Increment= 1
Transport Output Increment 1
XS Output Flag= 0
XS Output Increment= 10
Read HDF5 Sediment Hotstart= 0
Sediment Hotstart Type= 0
Write Gradation File= 0
Read Gradation Hotstart= 0
Write HDF5 File= 1
Write Binary Output= 1
Write DSS Sediment File= 0
DSS Sediment Output Type= 1
SV Curve= 0
Specific Gage Flag= 0
Subcell Erosion Methods= 0
Subcell Deposition Methods= 0
Advection Scheme= 1
Matrix Solver= 0
Implicit Weighting Factor= 1
Maximum Outer Loop Convergence Iterations= 5
Convergence Maximum Absolute= 0.001
Convergence RMSE= 0.0001
Grain Fractions Max Abs Error= 0.001
Max Subgrid Regions= 1
Max Subgrid Length Scale= 3.402823E+38
Initial Layer Thickness= 3.402823E+38
Min Layer Thickness= 3.402823E+38
Max Layer Thickness= 3.402823E+38
Number of Layers= 5

--- COLLINSRN.f01 (steady flow) ---

Flow Title=Flow
Program Version=6.20
Number of Profiles= 1
Profile Names=P100yr
River Rch & RM=COLLINSRN,Main            ,1646
     484
Boundary for River Rch & Prof#=COLLINSRN,Main            , 1
Up Type= 0
Dn Type= 3
Dn Slope=0.03733
DSS Import GetInterval= 0
DSS Import GetPeak= 0
DSS Import FillOption= 0

--- COLLINSRN.g01 (geometry) ---

Geom Title=Geometry
Program Version=6.20

River Reach=COLLINSRN       ,Main
Reach XY= 30
2408274.92574175722146.7953324172408258.70323034722163.214453593
2408238.77133204722172.5515223742408158.52206627722193.508337021
2408132.45383339722205.2645988762408099.74075688722223.665704429
 2408070.0945313 722247.178228172408000.91299999722362.421000019
2407964.97499998 722405.130000012407929.03799999722429.088000014
2407873.30899999722437.9420000022407769.66300002722441.067000002
2407695.18400003      722450.9632407678.51700003722462.422000006
2407664.97500002 722480.13000001     2407629.558722528.567000002
2407606.12100001722566.067000017     2407557.683722631.172000006
2407539.45400004      722644.7132407425.39199999722699.400999993
     2407292.058722780.6509999932407209.24600001722803.047000021
2407094.32990788722812.1216544212407075.91200002722816.588000014
 2407050.1944246722830.3399460912407013.41226302722858.101049855
2406988.96035829722867.8705028592406964.64597549722873.496135786
 2406936.7562004722876.6182266322406893.06478396722872.837408155

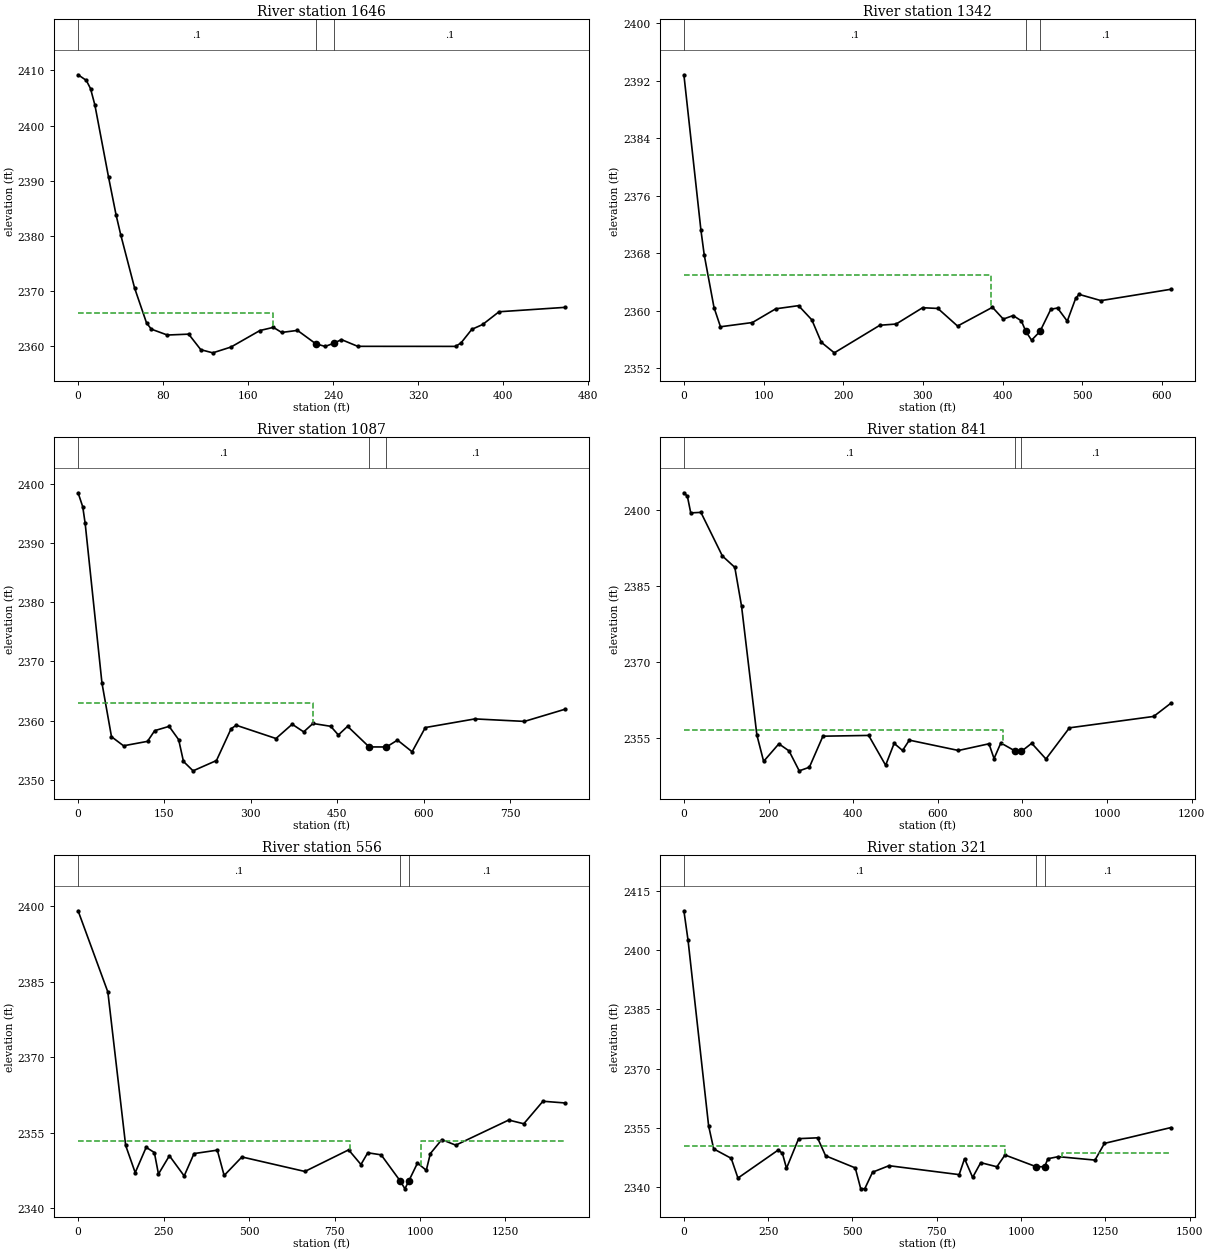
Type RM Length L Ch R = 1 ,1646    ,307.4,304,300.4
XS GIS Cut Line= 3
2408154.90344044721953.5770960762408165.42076185722019.485643568
2408409.42261852722325.890273929
#Sta/Elev= 30
       0  2409.2     7.7 2408.19    11.7  2406.7    15.8 2403.73    28.7 2390.61
    35.7 2383.84    40.1 2380.21    53.2 2370.52    64.4 2364.21    68.9 2363.07
      84    2362   104.1 2362.16   115.5 2359.34   126.8 2358.77   143.9 2359.82
   171.2 2362.82   183.8 2363.39   191.6 2362.47   206.5 2362.84   223.6 2360.43
   232.5 2359.93   240.7 2360.51   247.9 2361.17   263.2 2359.95   355.3 2359.94
   360.4 2360.56   370.6 2363.03   380.8 2363.91   396.2 2366.22 458.432 2367.02
#Mann= 3 ,-1,0
       0      .1       0   223.6    .045       0   240.7      .1       0
#XS Ineff= 2 , 0
           183.3    2366
Permanent Ineff=
       F       F
Bank Sta=223.6,240.7
XS Rating Curve= 0 ,0
Exp/Cntr(USF)=0,0
Exp/Cntr=0.3,0.1

Type RM Length L Ch R = 1 ,1342    ,237.8,255,261.4
XS GIS Cut Line= 3
2407972.60320269721952.1747865552407911.60273853 722250.86671455
2408181.54732134722396.005749984
#Sta/Elev= 30
       0 2392.82    21.4 2371.17    25.5 2367.76    37.8 2360.42    45.9 2357.74
      86 2358.33   115.3 2360.24   143.9 2360.68   160.6  2358.7   172.5 2355.58
   188.8 2354.11     246 2357.95   266.4 2358.12   299.6 2360.39   318.8 2360.29
   343.5 2357.84   387.3 2360.45   400.9 2358.81   413.3  2359.3   423.6 2358.56
  429.22 2357.09   436.4 2355.87  446.99 2357.09   460.6 2360.18     469 2360.35
   481.2 2358.52   491.7 2361.68     496 2362.25   523.5 2361.38611.3461 2362.96
#Mann= 3 ,0,0
       0      .1       0  429.22    .045       0  446.99      .1       0
#XS Ineff= 2 , 0
           385.3    2365
Permanent Ineff=
       F       F
Bank Sta=429.22,446.99
XS Rating Curve= 0 ,0
Exp/Cntr(USF)=0,0
Exp/Cntr=0.3,0.1

Type RM Length L Ch R = 1 ,1087    ,259.3,246.8,241.8
XS GIS Cut Line= 4
2407893.76697319721921.4036106922407811.93034161722205.146755868
2407831.78399106722463.4895410962408040.39353404722666.392913686
#Sta/Elev= 30
       0 2398.47     8.1  2396.1    12.3 2393.29    41.4 2366.37      58 2357.27
    78.9 2355.74   120.5 2356.49     133  2358.3     158 2359.02   174.6 2356.77
   182.9  2353.1   199.6 2351.51   240.2 2353.25   265.6 2358.62   274.5 2359.21
   343.5 2356.97   371.6 2359.38   391.6 2358.09   407.7 2359.51   438.5 2359.03
   451.8 2357.57   467.8 2359.03   505.22355.549   535.32355.541   554.4  2356.7
   579.8 2354.73   602.7 2358.82   688.8 2360.28   774.8 2359.86   845.4 2361.92
#Mann= 3 ,0,0
       0      .1       0   505.2    .045       0   535.3      .1       0
#XS Ineff= 2 , 0
           407.3    2363
Permanent Ineff=
       F       F
Bank Sta=505.2,535.3
XS Rating Curve= 0 ,0
Exp/Cntr=0.3,0.1

Type RM Length L Ch R = 1 ,841     ,282.7,285.2,286.5
XS GIS Cut Line= 3
2407566.82097709721756.9713503332407599.61635665722514.665417447
2407899.92533567722767.451792778
#Sta/Elev= 30
       0 2403.38     8.2  2402.7    16.2 2399.41    40.2 2399.51    90.9 2390.91
   120.3 2388.66   136.3 2380.96   172.4 2355.58   188.4 2350.36   224.4 2353.82
   248.4 2352.43   272.5 2348.49   296.5  2349.2   328.5 2355.33   436.6 2355.48
   476.7 2349.59   496.8 2353.91   516.7 2352.51   532.7 2354.55   648.8 2352.51
   720.9 2353.83   732.9 2350.91   748.9 2353.99   782.32352.424   797.72352.349
   821.9 2353.93   855.5 2350.83     911 2356.98  1110.1 2359.23  1150.9 2361.85
#Mann= 3 ,0,0
       0      .1       0   782.3    .045       0   797.7      .1       0
#XS Ineff= 2 , 0
          753.62 2356.65
Permanent Ineff=
       F       F
Bank Sta=782.3,797.7
XS Rating Curve= 0 ,0
Exp/Cntr(USF)=0,0
Exp/Cntr=0.3,0.1

Type RM Length L Ch R = 1 ,556     ,234.9,234.6,234.1
XS GIS Cut Line= 4
 2407381.1367611721770.1503483452407358.31998514722640.625158549
2407472.66019986722796.1776062942407833.00249749722780.107701505
#Sta/Elev= 30
       0  2399.1    87.1 2382.97   139.1 2352.52   167.1  2347.1   199.1 2352.13
   223.1  2351.1   235.1 2346.83   267.1 2350.46   310.3 2346.45   339.1 2350.89
   407.2 2351.57   427.2 2346.54   479.2 2350.22   663.3 2347.34   791.3 2351.63
   827.3 2348.72   847.3 2351.05   886.4 2350.64   942.7  2345.4   955.9 2343.89
   966.82345.395   992.7 2349.01  1018.4 2347.57  1030.3 2350.89  1063.8 2353.67
  1104.6 2352.56  1259.5 2357.55  1303.6 2356.81  1359.6 2361.28  1424.5 2360.94
#Mann= 3 ,0,0
       0      .1       0   942.7    .045       0   966.8      .1       0
#XS Ineff= 2 , 0
           796.1 2353.45 1001.85         2353.35
Permanent Ineff=
       F       F
Bank Sta=942.7,966.8
XS Rating Curve= 0 ,0
Exp/Cntr=0.3,0.1

Type RM Length L Ch R = 1 ,321     ,,,
XS GIS Cut Line= 4
2407124.06687078721764.9081786892407139.18977587722726.438223426
2407211.03754781722822.8047687242407572.89743268722797.629340482
#Sta/Elev= 30
       0 2409.97    12.3 2402.51    73.3 2355.52    88.3 2349.67   140.3 2347.28
   160.3 2342.28   280.3 2349.41   292.3 2348.51   304.3 2344.75   340.3 2352.26
   396.3 2352.47   420.3 2347.92   508.3 2344.85   524.3 2339.63   536.3 2339.55
   559.6 2343.77   608.3 2345.41   816.4 2343.15   832.4 2347.18   856.4 2342.45
   880.4 2346.18   928.4 2345.14   952.4 2348.13  1044.9 2345.15  1069.8 2345.15
  1079.8 2347.18  1110.7  2347.7  1219.3 2346.83  1247.4 2351.06  1444.6 2355.07
#Mann= 3 ,0,0
       0      .1       0  1044.9    .045       0  1069.8      .1       0
#XS Ineff= 2 , 0
           952.2 2350.36 1122.89         2348.54
Permanent Ineff=
       F       F
Bank Sta=1044.9,1069.8
XS Rating Curve= 0 ,0
Exp/Cntr=0.3,0.1
LCMann Table=0

Chan Stop Cuts=-1
Use User Specified Reach Order=0
Composite Channel Slope=5